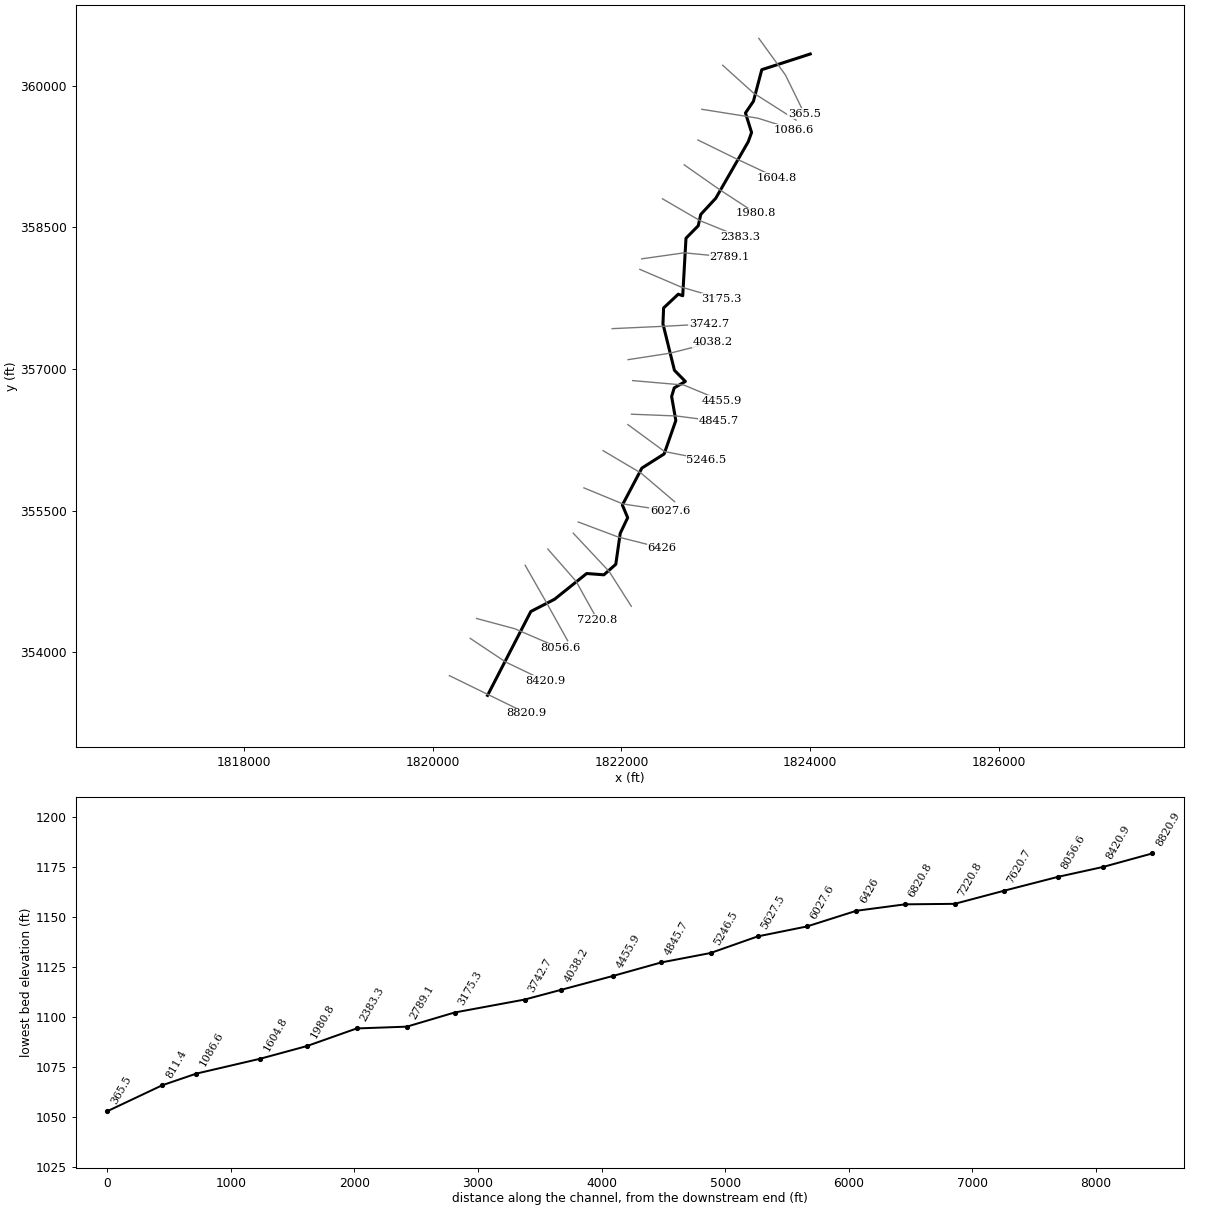
--- LckRn2.prj (project) ---

Proj Title=LckRn2
Current Plan=p01
Default Exp/Contr=0,0
English Units
Geom File=g01
Flow File=f01
Plan File=p01
BEGIN DESCRIPTION:
END DESCRIPTION:
DSS Export Rating Curves= 0
DSS Export Rating Curve Sorted= 0
DSS Export Volume Flow Curves= 0
DXF OffsetX= 0
DXF OffsetY= 0
DXF ScaleX= 0
DXF ScaleY= 0

--- LckRn2.p01 (plan) ---

Plan Title=Floodplain
Program Version=4.00
Geom File=g01
Flow File=f01
K Sum by GR=0
Std Step Tol=0.01
Critical Tol=0.01
Num of Std Step Trials=20
Max Error Tol=0.3
Flow Tol Ratio=0.001
Split Flow NTrial=30
Split Flow Tol=0.02
Split Flow Ratio=0.02
Log Output Level=0
Friction Slope Method=1
Unsteady Friction Slope Method=2
Unsteady Bridges Friction Slope Method=1
Global Log Level=0
CheckData=False
Run HTab=0
Run UNet=0
Run PostProcess=0
UNET Theta=0
UNET Theta Warmup=0
UNET ZTol=0
UNET ZSATol=0
UNET MxIter=0
UNET MaxInSteps=0
UNET DtIC=0
UNET DtMin=0
UNET MaxCRTS=0
UNET WFStab=0
UNET SFStab=0
UNET WFX=0
UNET SFX=0
UNET DSS MLevel=0
UNET DZMax Abort=0
UNET Convert EG Bridges=0
UNET Use Existing IB Tables=0
UNET Froude Limit=0
UNET Froude Power=0
Write IC File=0
Echo Input=False
Echo Output=False
Write Detailed=0

--- LckRn2.f01 (steady flow) ---

Flow Title=NFF Regression Equation
Program Version=4.00
Number of Profiles= 1
Profile Names=P100yr
River Rch & RM=LckRn2,Main            ,8820.9
  726.28
River Rch & RM=LckRn2,Main            ,8056.6
 739.018
River Rch & RM=LckRn2,Main            ,7620.7
820.4076
River Rch & RM=LckRn2,Main            ,6426
947.4134
River Rch & RM=LckRn2,Main            ,4038.2
1027.066
River Rch & RM=LckRn2,Main            ,3175.3
1140.782
River Rch & RM=LckRn2,Main            ,365.5
 1220.46
Boundary for River Rch & Prof#=LckRn2,Main            , 1
Up Type= 0
Dn Type= 3
Dn Slope=0.015854
DSS Import GetInterval= 0
DSS Import GetPeak= 0
DSS Import FillOption= 0

--- LckRn2.g01 (geometry) ---

Geom Title=USGS 3m DEM
Program Version=4.00

River Reach=LckRn2          ,Main
Reach XY= 30
     1820580.843       353541.74     1821039.427      354430.247
     1821290.503      354559.798     1821631.002      354832.656
     1821813.289      354818.898       1821939.4      354930.105
     1821986.404      355257.992      1822065.51      355424.229
     1822009.334      355558.365     1822215.697      355949.309
     1822451.868      356099.495     1822575.686      356453.752
     1822530.974      356708.266     1822558.913      356799.619
     1822676.574      356867.624     1822560.782       356985.71
     1822439.257      357477.542     1822446.136      357646.071
     1822601.173      357791.774     1822648.716      357775.926
     1822683.292      358384.857     1822812.954       358516.92
     1822839.847      358636.978      1822998.73      358808.583
     1823342.986      359407.544     1823378.187      359505.197
     1823313.463      359711.857     1823398.069      359836.498
     1823486.231      360170.445      1823999.59      360336.816

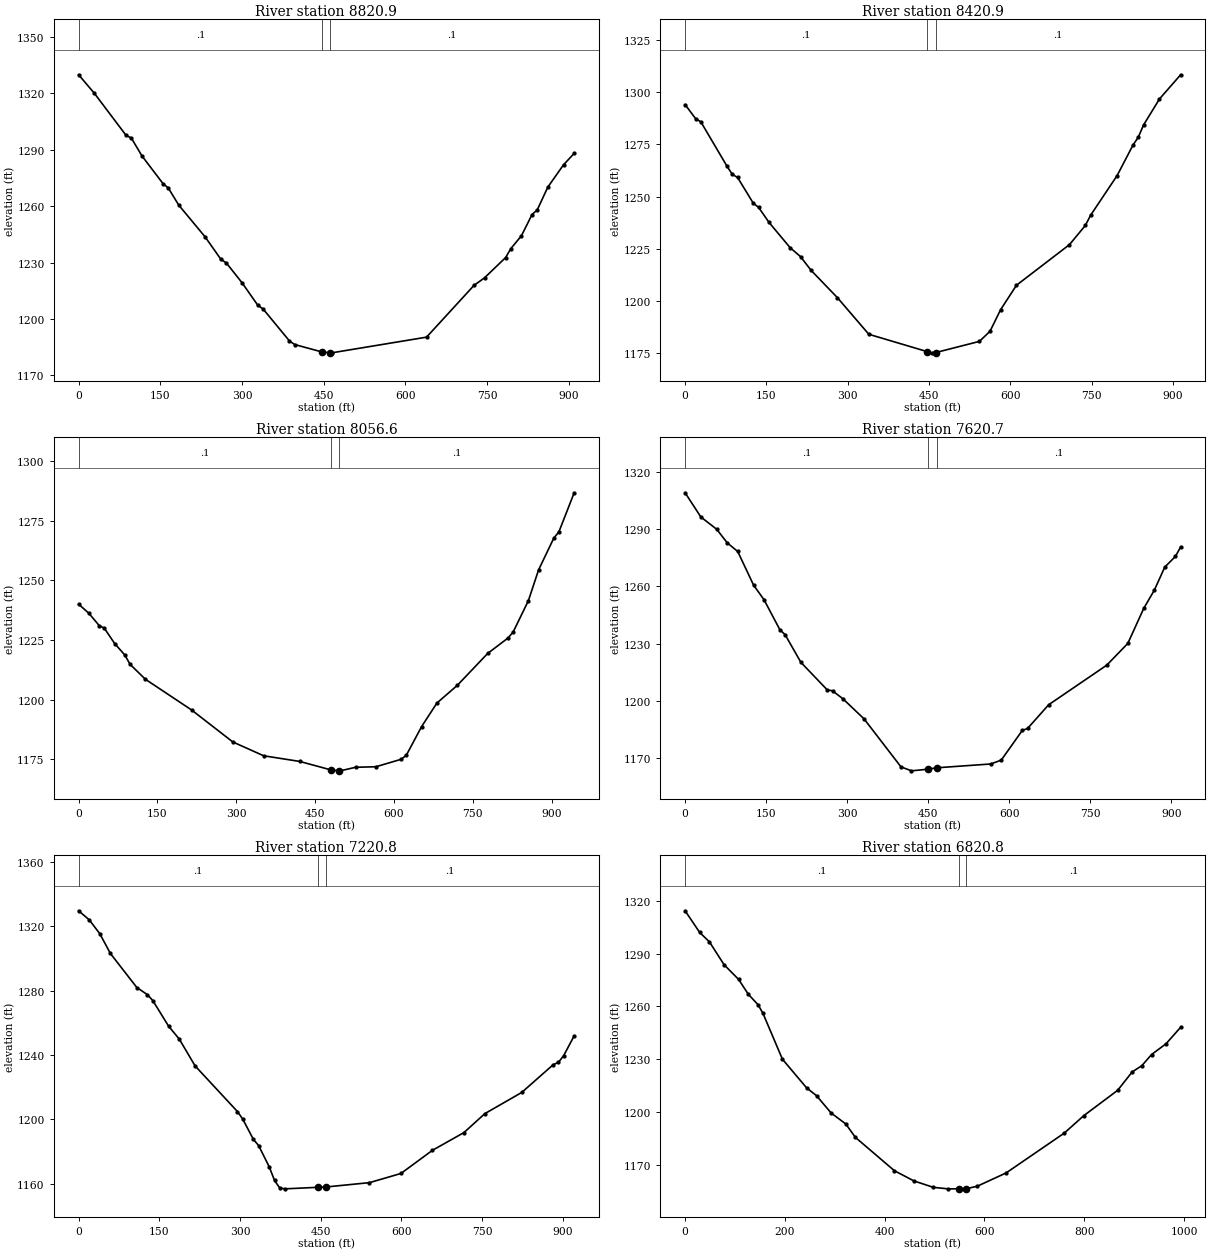
Type RM Length L Ch R = 1 ,8820.9  ,403.229,400.056,400.057
XS GIS Cut Line= 3
      1820176.95      353750.564     1820585.715      353550.724
      1820994.48      353350.884
#Sta/Elev= 30
       0 1329.93      29 1320.03    87.1 1297.68    96.8 1296.26   116.2 1286.78
   154.9 1272.01   164.6 1269.69   183.9 1260.53   232.3 1243.63   261.4 1231.64
   271.1 1229.82   300.1 1219.21   329.1 1207.22   338.8 1205.24   387.2 1188.22
   396.9 1186.32   447.1 1182.36   462.1 1181.92   464.7 1181.91   638.9 1190.26
   726.1 1217.83   745.4 1221.84   784.1 1232.63   793.8 1237.42   813.2 1244.25
   832.6 1255.53   842.2 1258.01   861.6 1270.12   890.6 1282.07     910 1288.09
#Mann= 3 , 0 , 0
       0      .1       0   447.1    .045       0   462.1      .1       0
Bank Sta=447.1,462.1
XS Rating Curve= 0 ,0
Exp/Cntr=0.3,0.1

Type RM Length L Ch R = 1 ,8420.9  ,360.236,364.229,365.049
XS GIS Cut Line= 3
     1820397.274      354145.413      1820775.87      353893.235
     1821189.799       353695.02
#Sta/Elev= 30
       0 1294.03    19.4 1287.29      29 1285.78    77.4 1264.45    87.1  1260.6
    96.8 1259.12   125.8 1246.76   135.5 1244.82   154.9 1237.56   193.6 1225.52
   212.9  1221.2   232.3 1214.65   280.7  1201.6   338.8 1184.02     447 1175.67
   454.9 1175.13     462 1175.25   542.8 1180.62   562.3 1185.47   581.8 1195.79
   611.1 1207.51   708.8 1226.96   738.1 1236.15   747.8 1241.03   796.7 1260.05
     826 1274.67   835.7  1278.4   845.5  1284.3   874.8 1296.74   913.8 1308.31
#Mann= 3 , 0 , 0
       0      .1       0     447    .045       0     462      .1       0
Bank Sta=447,462
XS Rating Curve= 0 ,0
Exp/Cntr=0.3,0.1

Type RM Length L Ch R = 1 ,8056.6  ,450.623,435.927,420.99
XS GIS Cut Line= 3
     1820464.374      354356.414     1820870.455      354247.176
     1821350.086      354040.206
#Sta/Elev= 30
       0 1240.04    19.6  1236.2    39.1 1231.08    48.9 1229.97    68.5 1223.56
      88 1218.71    97.8 1214.84   127.1 1208.56   215.1 1195.67   293.4 1182.29
   352.1  1176.5   420.5 1174.14   480.8 1170.54   495.8 1170.22   497.9 1170.19
   526.9 1171.68   565.6  1171.9     614 1175.05   623.7 1176.81   652.7 1188.77
   681.7  1198.6   720.4 1205.99   778.4 1219.41   817.1 1225.87   826.8 1228.38
   855.8 1241.52   875.2 1254.43   904.2 1267.75   913.9 1270.38   942.9 1286.73
#Mann= 3 , 0 , 0
       0      .1       0   480.8    .045       0   495.8      .1       0
Bank Sta=480.8,495.8
XS Rating Curve= 0 ,0
Exp/Cntr=0.3,0.1

Type RM Length L Ch R = 1 ,7620.7  ,395.262,399.938,400.063
XS GIS Cut Line= 3
     1820979.701       354919.66      1821206.51      354521.825
     1821429.717      354120.521
#Sta/Elev= 30
       0 1309.02    29.2 1296.32    58.5 1289.89    77.9  1282.8    97.4 1278.25
   126.7 1260.64   146.2 1252.88   175.4 1237.23   185.1 1234.63   214.4  1220.1
   263.1 1205.69   272.8 1205.22   292.3 1200.98   331.3 1190.47   399.5 1165.35
     419 1163.26   450.3 1164.15   465.3 1164.85   565.4 1166.85     585 1168.85
     624 1184.41   633.8 1185.48   672.9 1197.91   780.4 1218.66   819.4 1230.08
   848.8 1248.42   868.3 1257.91   887.8 1270.09   907.4 1275.63   917.1 1280.62
#Mann= 3 , 0 , 0
       0      .1       0   450.3    .045       0   465.3      .1       0
Bank Sta=450.3,465.3
XS Rating Curve= 0 ,0
Exp/Cntr=0.3,0.1

Type RM Length L Ch R = 1 ,7220.8  ,396.31,399.996,402.52
XS GIS Cut Line= 3
     1821219.291       355091.71     1821517.939      354751.582
     1821745.698      354342.275
#Sta/Elev= 30
       0 1329.62    19.7 1323.98    39.4 1315.34      59 1303.08   108.2  1281.9
   127.9 1277.45   137.8 1273.79   167.3 1257.81     187 1249.86   216.5 1233.14
   295.2 1204.76     305  1200.1   324.7 1187.53   334.6 1183.57   354.2 1170.42
   364.1 1161.93   373.9 1157.19   383.8 1156.71   444.8 1157.66   459.8 1157.87
   540.5 1160.56     599 1166.26   657.6 1180.67   716.1 1191.69   755.1  1203.5
   823.5 1216.64     882  1233.9   891.8 1235.38   901.5 1239.53     921 1251.88
#Mann= 3 , 0 , 0
       0      .1       0   444.8    .045       0   459.8      .1       0
Bank Sta=444.8,459.8
XS Rating Curve= 0 ,0
Exp/Cntr=0.3,0.1

Type RM Length L Ch R = 1 ,6820.8  ,382.535,394.775,411.934
XS GIS Cut Line= 3
     1821488.929      355259.992     1821869.289      354854.229
     1822103.984      354485.425
#Sta/Elev= 30
       0 1314.24    29.3 1301.92    48.8 1296.59    78.1 1283.65   107.3 1275.29
   126.8 1266.85   146.4 1260.87   156.1 1256.04   195.1 1230.02   243.9 1213.65
   263.4 1209.35   292.7  1199.5     322 1193.31   341.5 1185.63   419.6 1166.75
   458.6 1160.97   497.6 1157.32   526.9 1156.47   548.4 1156.48   563.4 1156.54
   585.3 1157.91   643.6 1165.51   760.2 1188.13     799 1197.95     867 1212.36
   896.2 1222.81   915.6 1226.37     935 1232.66   964.2 1238.83   993.3 1248.14
#Mann= 3 , 0 , 0
       0      .1       0   548.4    .045       0   563.4      .1       0
Bank Sta=548.4,563.4
XS Rating Curve= 0 ,0
Exp/Cntr=0.3,0.1

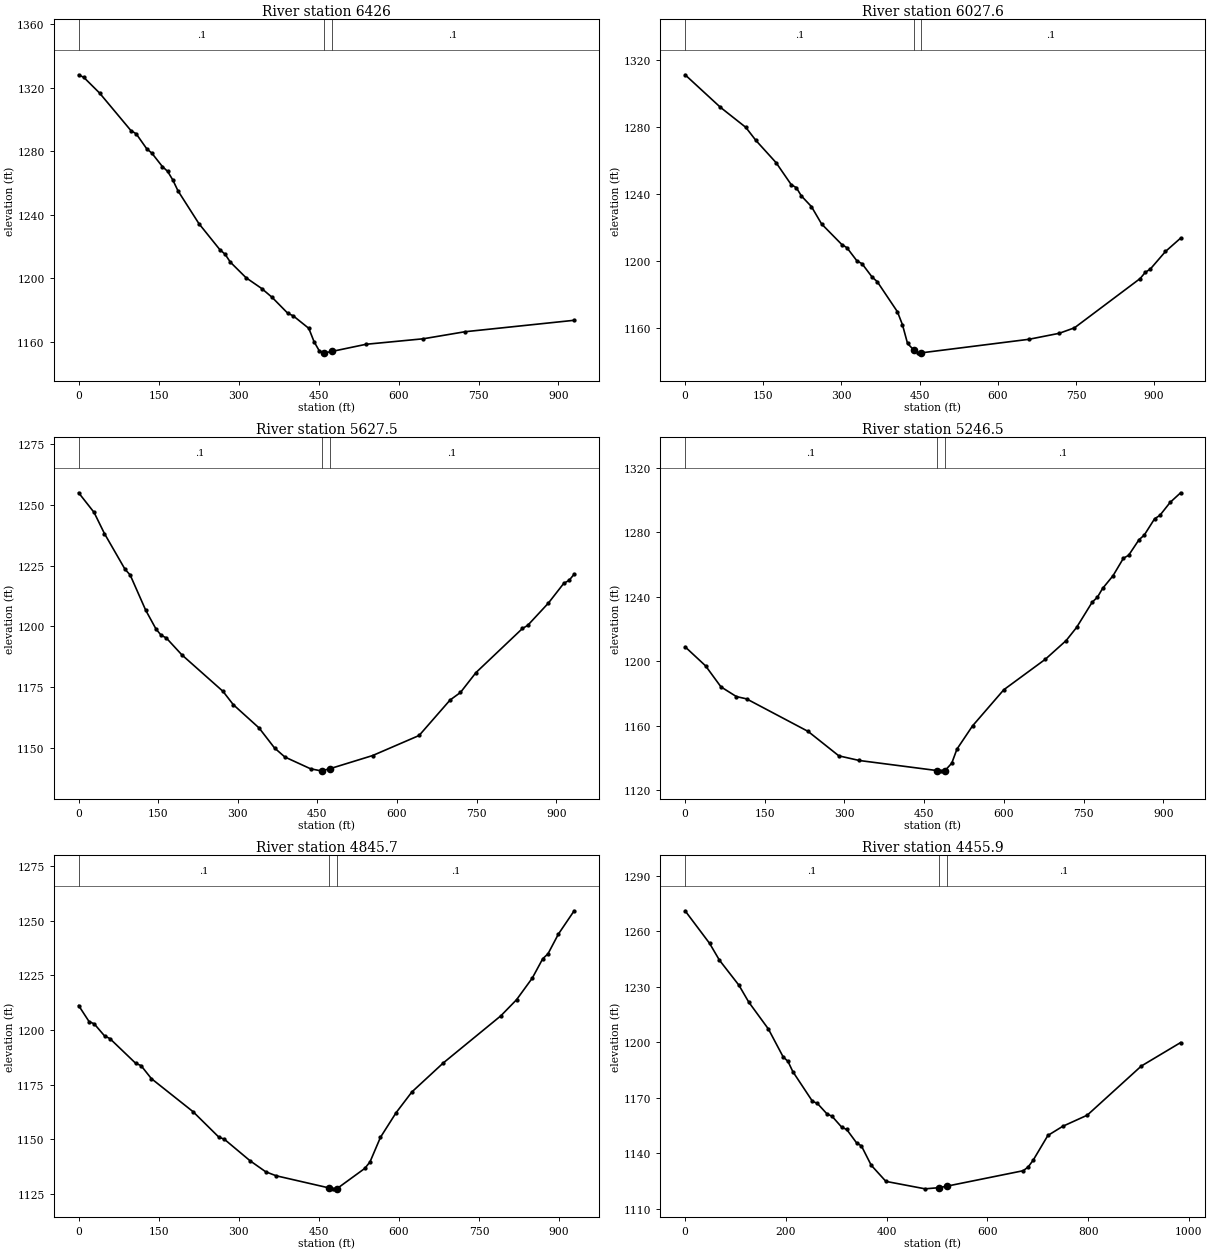
Type RM Length L Ch R = 1 ,6426    ,402.563,398.399,398.567
XS GIS Cut Line= 3
     1821541.691       355378.65     1821964.097      355219.668
     1822427.695      355102.994
#Sta/Elev= 30
       0 1328.03     9.8 1326.37    39.2 1316.58    98.1 1292.95   107.9 1290.95
   127.6 1281.58   137.4 1278.74     157 1270.37   166.8 1267.37   176.6 1261.93
   186.4 1255.05   225.7 1234.42   264.9 1218.09   274.7 1215.23   284.5 1210.28
     314 1200.46   343.4 1193.67     363 1188.09   392.5 1178.04   402.3 1176.55
   431.7 1168.64   441.5 1160.29   451.3 1154.53   460.2 1153.36   461.1 1153.25
   475.2 1154.14   539.1 1158.63   646.5 1162.09   724.5 1166.51   929.4 1173.71
#Mann= 3 , 0 , 0
       0      .1       0   460.2    .045       0   475.2      .1       0
Bank Sta=460.2,475.2
XS Rating Curve= 0 ,0
Exp/Cntr=0.3,0.1

Type RM Length L Ch R = 1 ,6027.6  ,400.427,400.073,386.07
XS GIS Cut Line= 3
     1821602.012      355739.992     1822014.514      355569.754
     1822513.473       355494.63
#Sta/Elev= 30
       0 1311.34    67.9  1291.9   116.4 1279.99   135.8 1272.19   174.6  1258.9
   203.7 1245.75   213.4    1244   223.1 1239.06   242.5 1232.66   261.9 1222.33
   300.7 1210.06   310.4  1208.2   329.8 1200.27   339.5 1198.63   358.9 1190.62
   368.6 1187.95   407.4 1169.95   417.1 1162.17   426.8 1151.04   438.3 1147.28
   446.3 1145.44   453.3 1145.44   659.7 1153.52   717.9  1157.1   747.1 1160.37
   873.2 1189.79   882.9 1193.45   892.6 1195.41   921.7 1205.91   950.8 1213.89
#Mann= 3 , 0 , 0
       0      .1       0   438.3    .045       0   453.3      .1       0
Bank Sta=438.3,453.3
XS Rating Curve= 0 ,0
Exp/Cntr=0.3,0.1

Type RM Length L Ch R = 1 ,5627.5  ,379.023,381.005,394.644
XS GIS Cut Line= 3
     1821805.051      356134.126     1822206.501      355896.938
     1822562.557      355593.968
#Sta/Elev= 30
       0 1254.98    29.1 1246.89    48.6  1238.2    87.4 1223.47    97.1 1221.13
   126.3 1206.65   145.7 1198.89   155.4 1196.32   165.1  1195.2   194.3 1188.27
     272 1173.19   291.4 1167.71     340 1158.11   369.1 1149.87   388.6 1146.14
   437.1 1141.28   456.6 1140.44   458.4 1140.48   473.4 1141.31   553.9 1146.73
   641.6    1155     700 1169.62   719.5 1172.72   748.7  1180.9   836.4 1199.09
   846.1 1200.33   885.1 1209.51   914.3  1217.7   924.1 1218.87   933.8 1221.45
#Mann= 3 , 0 , 0
       0      .1       0   458.4    .045       0   473.4      .1       0
Bank Sta=458.4,473.4
XS Rating Curve= 0 ,0
Exp/Cntr=0.3,0.1

Type RM Length L Ch R = 1 ,5246.5  ,386.626,400.845,402.585
XS GIS Cut Line= 3
     1822067.872      356410.182     1822456.541       356124.65
     1822898.535      356038.029
#Sta/Elev= 30
       0 1209.03    38.6 1197.21    67.5  1184.2    96.5 1178.19   115.7 1176.76
   231.5 1156.59   289.4 1141.44   327.9 1138.56   474.2 1132.32   482.3 1132.15
   489.2 1132.31   501.9 1136.89   511.7 1145.63     541 1160.01   599.8  1182.4
   678.1 1201.33   717.3 1212.93   736.9 1221.06   766.2 1236.69     776 1239.74
   785.8 1245.21   805.4 1253.07     825 1263.94   834.8 1265.76   854.3 1275.39
   864.1 1278.22   883.7 1288.41   893.5 1290.46   913.1 1298.61   932.7 1304.51
#Mann= 3 , 0 , 0
       0      .1       0   474.2    .045       0   489.2      .1       0
Bank Sta=474.2,489.2
XS Rating Curve= 0 ,0
Exp/Cntr=0.3,0.1

Type RM Length L Ch R = 1 ,4845.7  ,384.093,389.74,394.091
XS GIS Cut Line= 3
      1822105.56      356520.619     1822582.352      356501.694
     1823029.731      356443.969
#Sta/Elev= 30
       0 1211.24    19.5 1203.92    29.2 1202.86    48.7 1197.31    58.4 1196.16
   107.1 1184.77   116.9 1183.77   136.3 1177.81   214.2 1162.73   262.9    1151
   272.7 1150.14   321.4  1140.2   350.6 1135.19     370 1133.39   469.2 1127.82
   477.2 1127.41   484.2 1127.54     536 1136.74   545.8 1139.71   565.4 1150.96
   594.8 1162.26   624.3 1171.72   683.1 1184.98     791 1206.55   820.4 1213.91
   849.8 1223.78   869.4 1232.63   879.2 1234.86   898.8 1243.94   928.3 1254.57
#Mann= 3 , 0 , 0
       0      .1       0   469.2    .045       0   484.2      .1       0
Bank Sta=469.2,484.2
XS Rating Curve= 0 ,0
Exp/Cntr=0.3,0.1

Type RM Length L Ch R = 1 ,4455.9  ,415.498,417.78,421.329
XS GIS Cut Line= 3
     1822118.787      356876.545     1822661.139      356829.309
     1823066.759      356660.819
#Sta/Elev= 30
       0 1271.04    48.6 1253.42    68.1 1244.35   106.9 1230.76   126.4 1221.63
   165.3 1207.12   194.4 1192.14   204.2 1189.58   213.9 1184.03   252.8 1168.01
   262.5 1166.88   281.9 1161.12   291.6 1159.94   311.1 1153.93   320.8 1152.77
   340.3 1145.56     350 1143.88   369.4 1133.44   398.6  1124.7   476.4 1120.67
   504.7 1121.32   519.7 1122.12   671.3 1130.48   681.1 1132.55   690.8 1136.12
   720.1 1149.54   749.4 1154.46   798.2  1160.5   905.5 1187.07   983.6 1199.78
#Mann= 3 , 0 , 0
       0      .1       0   504.7    .045       0   519.7      .1       0
Bank Sta=504.7,519.7
XS Rating Curve= 0 ,0
Exp/Cntr=0.3,0.1

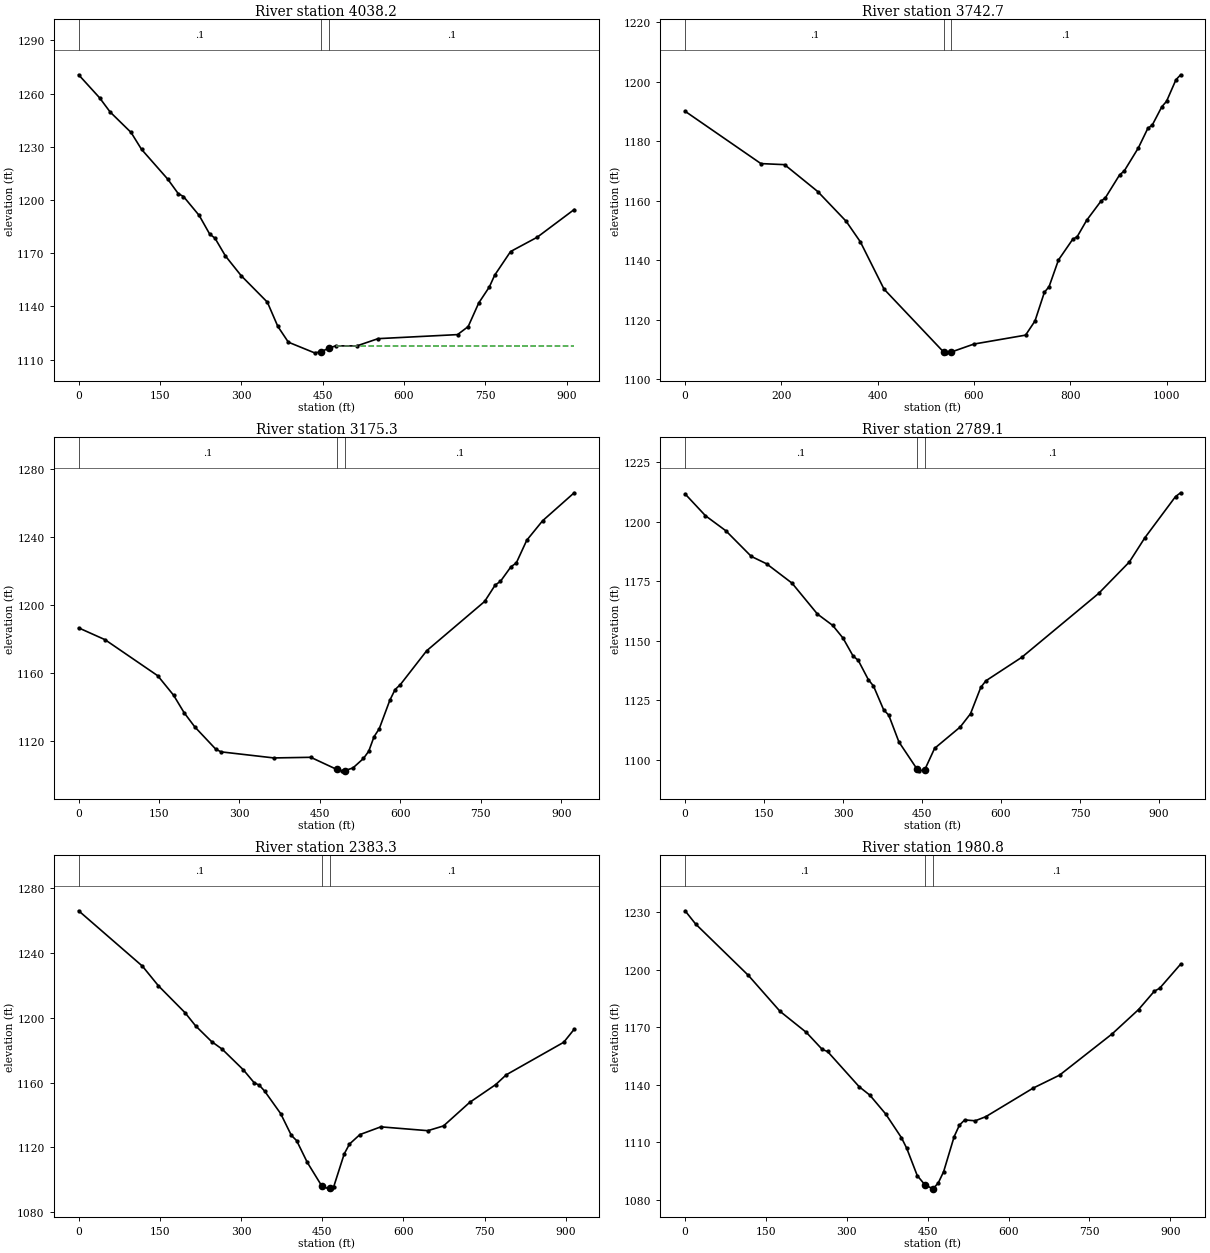
Type RM Length L Ch R = 1 ,4038.2  ,297.89,295.466,290.875
XS GIS Cut Line= 3
     1822070.437       357098.48     1822519.596        357167.8
     1822964.784      357281.857
#Sta/Elev= 30
       0 1270.56    38.7 1257.56      58 1249.61    96.7 1238.04     116 1228.52
   164.4  1211.7   183.7 1203.55   193.4 1201.92   222.4 1191.22   241.7 1180.74
   251.4 1178.46   270.8 1168.38   299.8 1157.28   348.1 1142.34   367.4 1128.68
   386.8 1119.79   435.1 1113.77   446.5 1114.35   461.5 1116.39     474  1117.7
   513.1 1117.68   552.3 1121.77   698.9 1124.05   718.5 1128.58     738  1141.9
   757.6 1150.95   767.4 1157.56   796.7 1170.89   845.6 1178.92     914 1194.57
#Mann= 3 , 0 , 0
       0      .1       0   446.5    .045       0   461.5      .1       0
#XS Ineff= 2 , 0
                          474.94         1117.76
Permanent Ineff=
       F       F
Bank Sta=446.5,461.5
XS Rating Curve= 0 ,0
Exp/Cntr=0.3,0.1

Type RM Length L Ch R = 1 ,3742.7  ,557.869,567.431,554.768
XS GIS Cut Line= 3
     1821901.092      357426.953      1822471.03      357453.075
     1822928.907      357477.491
#Sta/Elev= 30
       0 1190.07   157.4 1172.49   206.6 1172.13   275.4 1163.11   334.5  1153.1
     364 1146.19   413.1 1130.32     537 1109.15     541  1108.9     552 1109.13
   599.8 1111.85   707.1 1114.85   726.6  1119.6   746.1 1129.23   755.9 1131.15
   775.4 1140.11   804.7 1146.99   814.4 1147.96   833.9 1153.43   863.2 1159.78
     873 1161.05   902.2 1168.66     912 1170.02   941.3 1177.77   960.8 1184.28
   970.5 1185.53     990 1191.58   999.8 1193.41  1019.3 1200.64  1029.1 1202.33
#Mann= 3 , 0 , 0
       0      .1       0     537    .045       0     552      .1       0
Bank Sta=537,552
XS Rating Curve= 0 ,0
Exp/Cntr=0.3,0.1

Type RM Length L Ch R = 1 ,3175.3  ,375.174,386.112,392.225
XS GIS Cut Line= 3
     1822194.485      358054.937     1822628.667      357869.057
      1823062.25      357741.533
#Sta/Elev= 30
       0 1186.41    49.2 1179.47   147.6 1158.27   177.1 1146.84   196.8 1136.54
   216.5 1128.29   255.8 1115.14   265.7 1113.57   364.1    1110   432.9 1110.37
   481.4 1103.26   491.9 1102.42   496.4 1102.55   511.6 1104.11   531.2 1109.68
   541.1 1113.97   550.9 1122.44   560.7 1127.19   580.4 1143.89   590.2 1150.17
     600 1153.07   649.1 1172.96   757.2 1201.92   776.9 1211.57   786.7 1213.74
   806.3 1222.31   816.2  1224.5   835.8  1237.9   865.3 1249.32   924.2 1265.77
#Mann= 3 , 0 , 0
       0      .1       0   481.4    .045       0   496.4      .1       0
Bank Sta=481.4,496.4
XS Rating Curve= 0 ,0
Exp/Cntr=0.3,0.1

Type RM Length L Ch R = 1 ,2789.1  ,421.071,405.878,397.273
XS GIS Cut Line= 3
     1822213.423      358166.381     1822663.363      358230.455
     1823147.829      358183.735
#Sta/Elev= 30
       0 1211.63    38.7 1202.47    77.4 1196.16   125.7  1185.4   154.7  1182.3
   203.1 1174.17   251.4 1161.18   280.4 1156.41   299.8 1151.14   319.1 1143.56
   328.8 1141.78   348.1 1133.62   357.8 1130.99   377.1 1120.99   386.8 1118.74
   406.1  1107.5   440.3 1096.18   444.8 1095.36   455.3 1095.87   473.9  1104.8
   522.6 1113.78   542.1 1119.34   561.6  1130.4   571.3 1133.17   639.4 1143.02
   785.4 1169.84   843.8 1183.06   873.1 1193.18   931.5 1210.53   941.2 1212.11
#Mann= 3 , 0 , 0
       0      .1       0   440.3    .045       0   455.3      .1       0
Bank Sta=440.3,455.3
XS Rating Curve= 0 ,0
Exp/Cntr=0.3,0.1

Type RM Length L Ch R = 1 ,2383.3  ,404.147,402.516,398.678
XS GIS Cut Line= 3
     1822434.062      358802.707     1822833.124      358570.457
     1823253.673      358399.778
#Sta/Elev= 30
       0 1265.95   117.9 1231.79   147.4 1219.69   196.5 1203.13   216.1 1194.99
   245.6 1185.31   265.2 1180.61   304.5 1167.81   324.2 1159.95     334 1158.34
   343.8 1154.67   373.3 1140.86     393 1127.45   402.8  1124.2   422.4 1110.82
     449 1096.37   461.7 1094.46     464 1094.79   471.4 1095.86   490.7 1115.98
   500.4 1122.07   519.7 1127.92   558.3 1132.69   645.2 1130.33   674.2 1133.26
   722.5 1147.77   770.7 1158.77   790.1 1164.79   896.3 1184.85   915.6 1192.88
#Mann= 3 , 0 , 0
       0      .1       0     449    .045       0     464      .1       0
Bank Sta=449,464
XS Rating Curve= 0 ,0
Exp/Cntr=0.3,0.1

Type RM Length L Ch R = 1 ,1980.8  ,372.311,375.902,379.363
XS GIS Cut Line= 3
     1822664.605       359162.26      1823041.42      358898.297
      1823425.91      358647.109
#Sta/Elev= 30
       0 1230.72    19.6  1223.8   117.5 1196.98   176.2 1178.24   225.1 1167.23
   254.5 1158.37   264.3 1157.31     323 1138.92   342.6 1134.57     372 1124.76
   401.3 1112.37   411.1 1106.86   430.7 1092.55   445.3 1087.63   460.1 1085.66
   460.3 1085.73   469.8 1088.81   479.6 1094.61   499.2 1112.93   508.9 1118.89
   518.7 1121.61   538.2 1121.16   557.8  1123.3   645.7 1138.22   694.6 1144.96
   792.3 1166.51   841.2 1179.18   870.5 1188.77   880.3 1190.27   919.3 1202.88
#Mann= 3 , 0 , 0
       0      .1       0   445.3    .045       0   460.3      .1       0
Bank Sta=445.3,460.3
XS Rating Curve= 0 ,0
Exp/Cntr=0.3,0.1

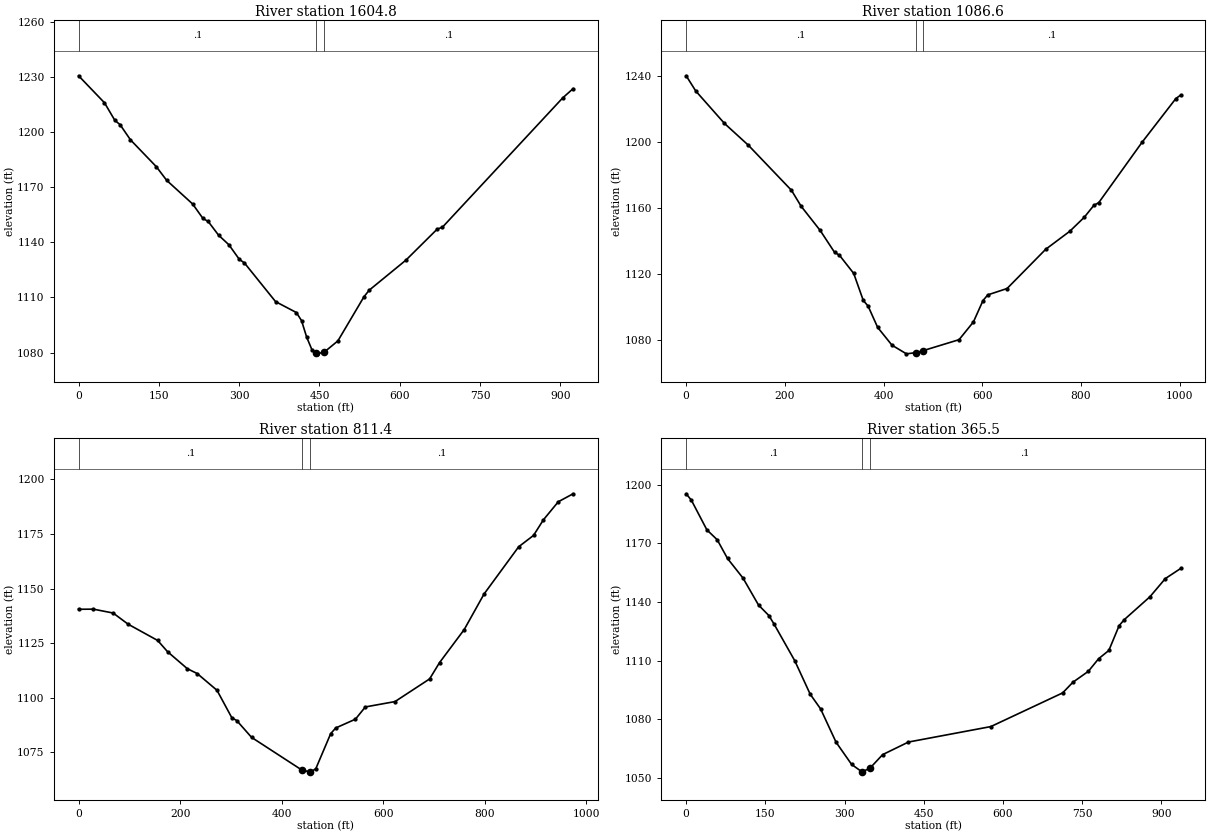
Type RM Length L Ch R = 1 ,1604.8  ,511.13,518.228,524.957
XS GIS Cut Line= 3
     1822810.031      359425.644     1823218.708      359225.159
     1823643.445      359026.885
#Sta/Elev= 30
       0  1230.5    48.4 1215.82    67.8 1206.25    77.5 1203.94    96.9  1195.7
   145.3 1181.07   164.6 1173.66   213.1 1160.81   232.4 1152.93   242.1 1151.33
   261.5 1143.88   280.9 1138.62   300.2 1130.76   309.9 1128.75     368 1107.75
   406.8 1101.83   416.5 1097.45   426.1 1088.47   435.8  1081.7   444.3 1079.65
   445.5 1079.36   459.3 1080.38   484.5 1086.41   533.3 1110.43   543.1 1113.99
   611.5 1130.27     670 1147.15   679.8  1148.2   904.4 1218.45   923.9 1223.51
#Mann= 3 , 0 , 0
       0      .1       0   444.3    .045       0   459.3      .1       0
Bank Sta=444.3,459.3
XS Rating Curve= 0 ,0
Exp/Cntr=0.3,0.1

Type RM Length L Ch R = 1 ,1086.6  ,287.056,275.249,266.151
XS GIS Cut Line= 3
     1822850.628      359751.064     1823444.673      359656.834
     1823826.752      359536.357
#Sta/Elev= 30
       0 1239.94    19.4 1230.75    77.6 1211.14   126.1 1197.95   213.4 1170.72
   232.8 1161.15   271.6 1146.45   300.7 1133.24   310.4 1131.56   339.5  1120.5
   358.9 1104.16   368.6 1100.78     388 1087.89   417.1 1077.12   446.3  1071.9
   465.9 1072.63   480.9  1073.9     553 1080.46   582.1 1091.19   601.5  1104.1
   611.2 1107.53   650.3 1111.38   728.5 1135.07   777.4 1145.98   806.7 1154.43
   826.2 1161.64     836 1163.25   923.9 1199.78   992.3 1226.18  1002.1 1228.26
#Mann= 3 , 0 , 0
       0      .1       0   465.9    .045       0   480.9      .1       0
Bank Sta=465.9,480.9
XS Rating Curve= 0 ,0
Exp/Cntr=0.3,0.1

Type RM Length L Ch R = 1 ,811.4   ,451.817,445.905,437.284
XS GIS Cut Line= 3
     1823072.136      360217.198     1823397.544      359923.901
      1823849.72      359636.225
#Sta/Elev= 30
       0 1140.54    29.2 1140.59    68.1 1138.81    97.4 1133.73   155.8 1126.25
   175.2 1121.12   214.2 1113.33   233.6 1111.12   272.6 1103.45   301.8 1090.89
   311.5 1089.59   340.7 1081.89   440.4 1066.84   455.4 1066.12   457.6 1066.11
   467.3 1067.57   496.5 1083.57   506.3 1086.17   545.3 1090.22   564.8 1095.82
   623.2 1098.27   691.4 1108.65   710.9  1116.1   759.6 1131.27   798.6 1147.52
   866.8 1169.15   896.1 1174.35   915.5 1181.48   944.8 1189.75     974 1193.41
#Mann= 3 , 0 , 0
       0      .1       0   440.4    .045       0   455.4      .1       0
Bank Sta=440.4,455.4
XS Rating Curve= 0 ,0
Exp/Cntr=0.3,0.1

Type RM Length L Ch R = 1 ,365.5   ,378.982,365.467,351.952
XS GIS Cut Line= 3
     1823454.822      360502.743     1823736.854      360114.523
     1823937.952      359704.158
#Sta/Elev= 30
       0  1195.3     9.8 1192.05    39.2 1176.86    58.8 1171.79    78.3 1162.22
   107.7 1152.17   137.1 1138.38   156.7 1133.02   166.5 1128.65   205.7 1109.93
     235 1092.78   254.6 1085.32     284 1068.23   313.4 1056.89   332.9 1053.11
     333  1053.1   347.9 1054.89   372.1 1061.89   421.1 1068.34   577.1 1076.24
   713.2 1093.47   732.7 1098.94   761.8 1104.49   781.3 1110.94   800.7 1115.18
   820.2 1127.87   829.9 1130.93   878.5 1142.62   907.7 1151.93   936.8 1157.11
#Mann= 3 , 0 , 0
       0      .1       0   332.9    .045       0   347.9      .1       0
Bank Sta=332.9,347.9
XS Rating Curve= 0 ,0
Exp/Cntr=0.3,0.1

Chan Stop Cuts=-1
Use User Specified Reach Order=0